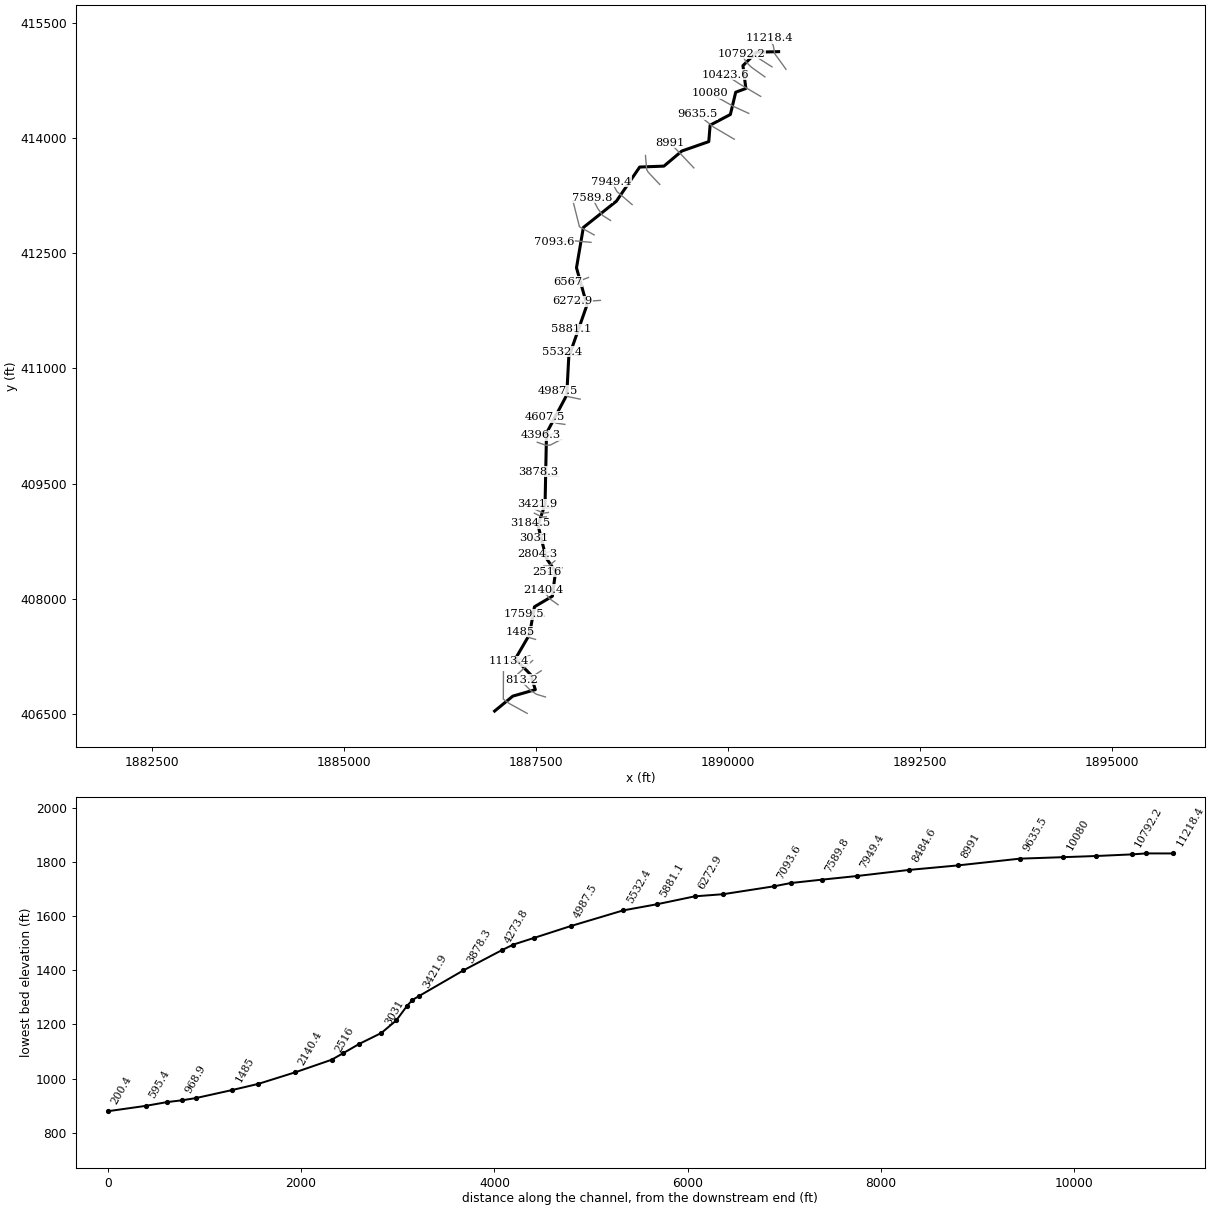
--- SCOTTRN.prj (project) ---

Proj Title=SCOTTRN
Current Plan=p01
Default Exp/Contr=0,0
English Units
Geom File=g01
Flow File=f01
Plan File=p01
BEGIN DESCRIPTION:
END DESCRIPTION:
DSS Export Rating Curves= 0
DSS Export Rating Curve Sorted= 0
DSS Export Volume Flow Curves= 0
DXF OffsetX= 0
DXF OffsetY= 0
DXF ScaleX= 0
DXF ScaleY= 0

--- SCOTTRN.p01 (plan) ---

Plan Title=Floodplain
Program Version=4.00
Geom File=g01
Flow File=f01
K Sum by GR=0
Std Step Tol=0.01
Critical Tol=0.01
Num of Std Step Trials=20
Max Error Tol=0.3
Flow Tol Ratio=0.001
Split Flow NTrial=30
Split Flow Tol=0.02
Split Flow Ratio=0.02
Log Output Level=0
Friction Slope Method=1
Unsteady Friction Slope Method=2
Unsteady Bridges Friction Slope Method=1
Global Log Level=0
CheckData=False
Run HTab=0
Run UNet=0
Run PostProcess=0
UNET Theta=0
UNET Theta Warmup=0
UNET ZTol=0
UNET ZSATol=0
UNET MxIter=0
UNET MaxInSteps=0
UNET DtIC=0
UNET DtMin=0
UNET MaxCRTS=0
UNET WFStab=0
UNET SFStab=0
UNET WFX=0
UNET SFX=0
UNET DSS MLevel=0
UNET DZMax Abort=0
UNET Convert EG Bridges=0
UNET Use Existing IB Tables=0
UNET Froude Limit=0
UNET Froude Power=0
Write IC File=0
Echo Input=False
Echo Output=False
Write Detailed=0

--- SCOTTRN.f01 (steady flow) ---

Flow Title=NFF Regression Equation
Program Version=4.00
Number of Profiles=1
Profile Names=P100yr
River Rch & RM=SCOTTRN,Main      ,11218.4
530.9377
River Rch & RM=SCOTTRN,Main      ,7265.3
587.2128
River Rch & RM=SCOTTRN,Main      ,7093.6
694.1931
River Rch & RM=SCOTTRN,Main      ,3421.9
761.2716
River Rch & RM=SCOTTRN,Main      ,200.4
824.5598
Boundary for River Rch & Prof#=SCOTTRN,Main      ,1
Up Type=0
Dn Type=3
Dn Slope=0.051957

--- SCOTTRN.g01 (geometry) ---

Geom Title=USGS 10m DEM
Program Version=4.10

River Reach=SCOTTRN         ,Main
Reach XY= 30
     1890661.342      415122.291     1890373.979       415115.01
     1890197.113      414940.314      1890235.09      414643.005
     1890102.712      414594.176     1890033.267      414304.463
     1889769.595      414165.574     1889752.234      413951.815
      1889401.83      413829.479     1889168.467      413632.805
     1888852.712      413620.869     1888549.977      413177.076
     1888119.205      412834.194     1888029.871      412310.027
     1888165.863      411825.079     1887929.318      411147.996
     1887903.276      410654.289     1887639.373       410158.42
     1887620.796      409232.704     1887528.782      408960.134
     1887634.685      408533.919     1887757.081      408356.836
     1887716.282      408037.391       1887482.8       407899.09
     1887418.539      407539.127     1887233.891      407221.266
      1887431.56      407018.294      1887494.06      406821.245
     1887200.498      406736.649     1886964.016      406542.455

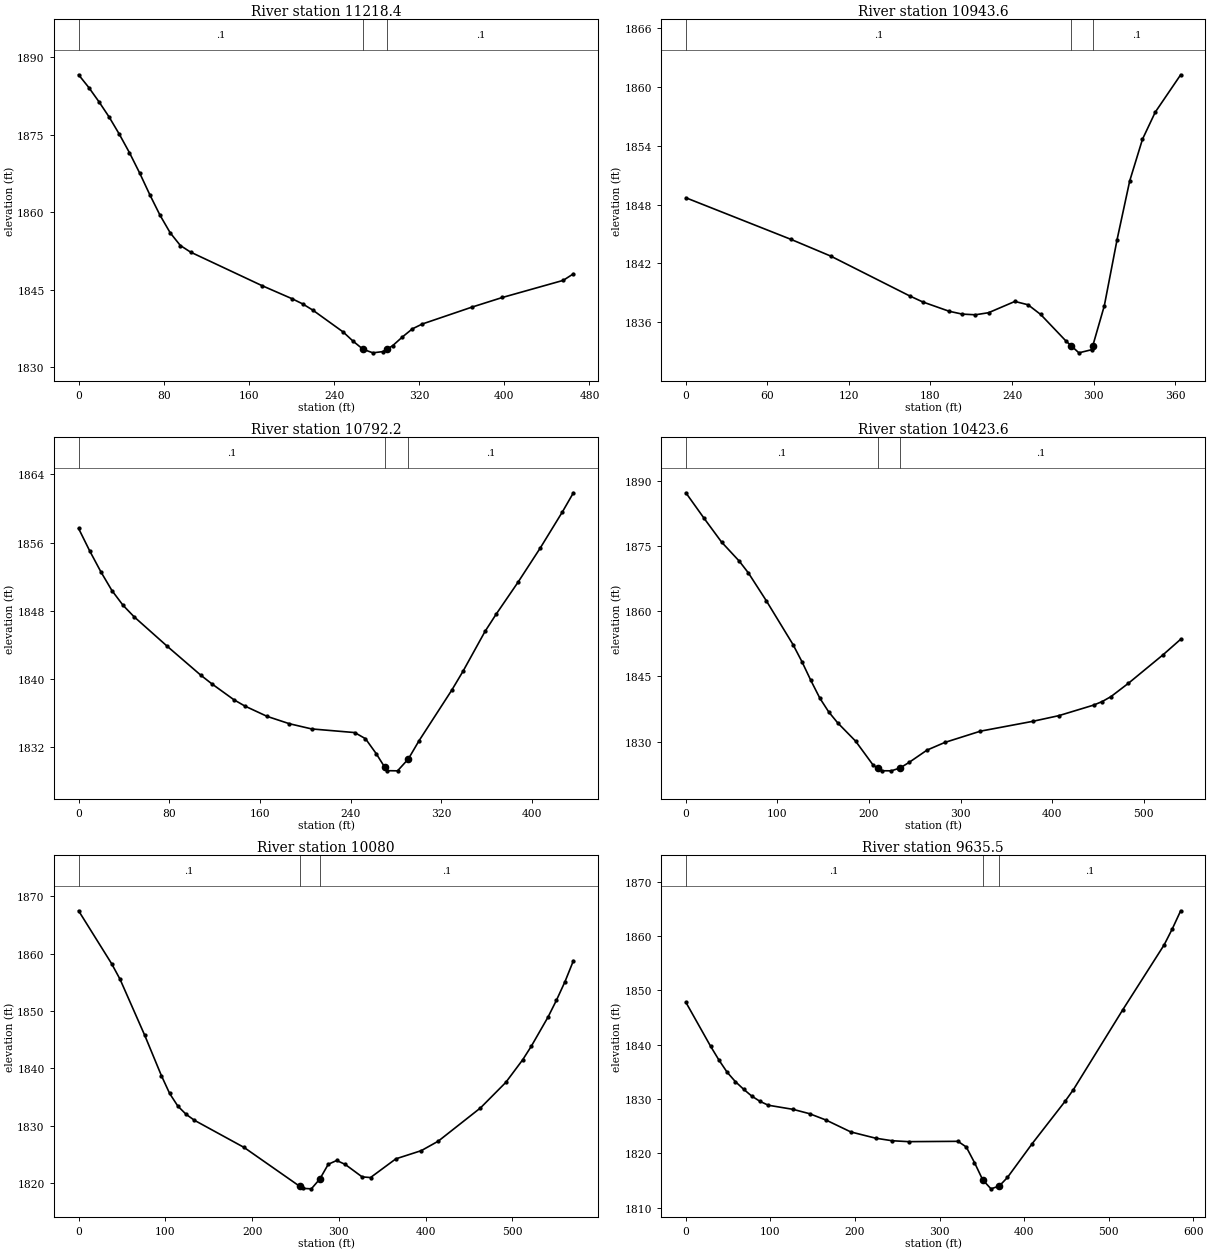
Type RM Length L Ch R = 1 ,11218.4 ,265.4,274.7,284.1
XS GIS Cut Line= 4
     1890757.819      414892.657     1890611.985      415094.046
     1890591.152      415203.421     1890540.805      415295.435
#Sta/Elev= 30
       0 1886.64     9.6 1884.17    19.1 1881.42    28.7 1878.45    38.2 1875.14
    47.8 1871.53    57.4 1867.58    66.9 1863.39    76.5 1859.41    86.1 1855.99
    95.6 1853.54   105.2 1852.26   172.1 1845.78   200.8  1843.2   210.4 1842.23
     220 1841.02   248.6 1836.77   257.9 1834.99   267.2 1833.43   276.5 1832.73
   285.8 1832.97  290.221833.513     295  1834.1   304.3 1835.82   313.6 1837.38
   322.9 1838.32   369.5 1841.59   398.1 1843.46   455.3 1846.78   464.9 1848.05
#Mann= 3 , 0 , 0
       0      .1       0   267.2    .045       0  290.22      .1       0
Bank Sta=267.2,290.22
XS Rating Curve= 0 ,0
Exp/Cntr=0.3,0.1

Type RM Length L Ch R = 1 ,10943.6 ,146.9,151.4,155.8
XS GIS Cut Line= 3
     1890575.223      414924.595     1890362.984      415060.011
     1890299.182      415152.459
#Sta/Elev= 23
       0  1848.7    77.5 1844.45   106.5 1842.76   164.6  1838.7   174.3 1838.08
   193.7 1837.13   203.3 1836.84     213 1836.77   222.7 1836.98   242.1 1838.13
   251.8 1837.79   261.1  1836.8   279.8 1834.08   283.7 1833.59   289.2 1832.89
   298.6 1833.21  299.371833.582   307.9 1837.68   317.3 1844.43   326.6 1850.42
     336 1854.67   345.4 1857.43   364.1 1861.24
#Mann= 3 , 0 , 0
       0      .1       0   283.7    .045       0  299.37      .1       0
Bank Sta=283.7,299.37
XS Rating Curve= 0 ,0
Exp/Cntr=0.3,0.1

Type RM Length L Ch R = 1 ,10792.2 ,363.3,368.6,371.1
XS GIS Cut Line= 4
     1890483.513      414793.699     1890308.166      414918.699
     1890240.458      414984.671     1890176.222      415094.046
#Sta/Elev= 30
       0 1857.65     9.8 1855.02    19.6 1852.58    29.4 1850.37    39.2 1848.64
    48.9  1847.3    78.3 1843.82   107.7 1840.45   117.5 1839.43     137 1837.56
   146.8 1836.81   166.4  1835.6     186 1834.74   205.6 1834.13   243.7  1833.7
   253.2 1832.98   262.6 1831.24  270.02 1829.67   272.1 1829.23   281.5 1829.21
     291  1830.6   300.4 1832.73   329.4 1838.69   339.2 1840.88   358.7 1845.57
   368.4 1847.57   387.9 1851.36   407.4 1855.35     427  1859.6   436.7 1861.84
#Mann= 3 , 0 , 0
       0      .1       0  270.02    .045       0     291      .1       0
Bank Sta=270.02,291
XS Rating Curve= 0 ,0
Exp/Cntr=0.3,0.1

Type RM Length L Ch R = 1 ,10423.6 ,343.4,343.6,345.8
XS GIS Cut Line= 3
     1890427.958      414540.227      1890158.86      414698.213
     1889967.888      414823.213
#Sta/Elev= 30
       0 1887.28    19.5 1881.52      39 1875.93    58.5  1871.5    68.3 1868.82
    87.8 1862.44     117 1852.34   126.8 1848.38   136.5 1844.07   146.3    1840
     156 1836.83   165.8 1834.31   185.3 1830.12   204.8  1824.5  210.221823.824
   214.5 1823.29   224.3 1823.27     234 1823.94   243.8 1825.22   263.3 1828.04
   282.8 1829.81   321.6  1832.4   378.6 1834.66   407.2 1835.97   445.2  1838.4
   454.7 1839.23   464.2 1840.36   483.2 1843.42   521.3 1850.03   540.3 1853.56
#Mann= 3 , 0 , 0
       0      .1       0  210.22    .045       0     234      .1       0
Bank Sta=210.22,234
XS Rating Curve= 0 ,0
Exp/Cntr=0.3,0.1

Type RM Length L Ch R = 1 ,10080   ,449.3,444.5,439.1
XS GIS Cut Line= 3
     1890272.272      414319.234       1890081.3       414406.04
     1889766.629      414581.821
#Sta/Elev= 30
       0  1867.5    38.1 1858.25    47.7 1855.56    76.3 1845.72    95.4 1838.72
   104.9  1835.6   114.4 1833.38     124 1831.94   133.5 1830.91   190.7 1826.17
  255.081819.352   258.5 1819.02   268.2 1818.94     278 1820.66   287.7 1823.23
   297.4 1823.89   307.2 1823.21   326.7 1821.03   336.4 1820.91   365.6 1824.18
   394.9 1825.61   414.4 1827.26   463.1 1833.07   492.3 1837.53   511.8 1841.49
   521.5  1843.8     541 1848.95   550.7 1851.89   560.5 1855.12   570.2 1858.78
#Mann= 3 , 0 , 0
       0      .1       0  255.08    .045       0     278      .1       0
#XS Ineff= 2 , 0
                          298.43         1823.77
Permanent Ineff=
       F       F
Bank Sta=255.08,278
XS Rating Curve= 0 ,0
Exp/Cntr=0.3,0.1

Type RM Length L Ch R = 1 ,9635.5  ,647.1,644.5,641.6
XS GIS Cut Line= 3
     1890084.208      413982.935      1889815.11      414140.921
     1889601.569       414311.06
#Sta/Elev= 30
       0  1847.8    29.2 1839.72      39  1837.2    48.8 1834.93    58.5 1833.21
    68.3  1831.8      78 1830.53    87.8 1829.56    97.5 1828.86   126.8  1828.1
   146.3  1827.3   165.8 1826.13     195 1823.95   224.3  1822.8   243.8 1822.33
   263.3 1822.16   321.8 1822.22   331.6 1821.17   341.3 1818.31     351 1815.14
   360.8 1813.48   370.6    1814   380.3 1815.58   409.6 1821.81   448.6 1829.62
   458.3 1831.74   516.8 1846.46   565.6 1858.37   575.3 1861.34   585.1 1864.63
#Mann= 3 , 0 , 0
       0      .1       0     351    .045       0   370.6      .1       0
Bank Sta=351,370.6
XS Rating Curve= 0 ,0
Exp/Cntr=0.3,0.1

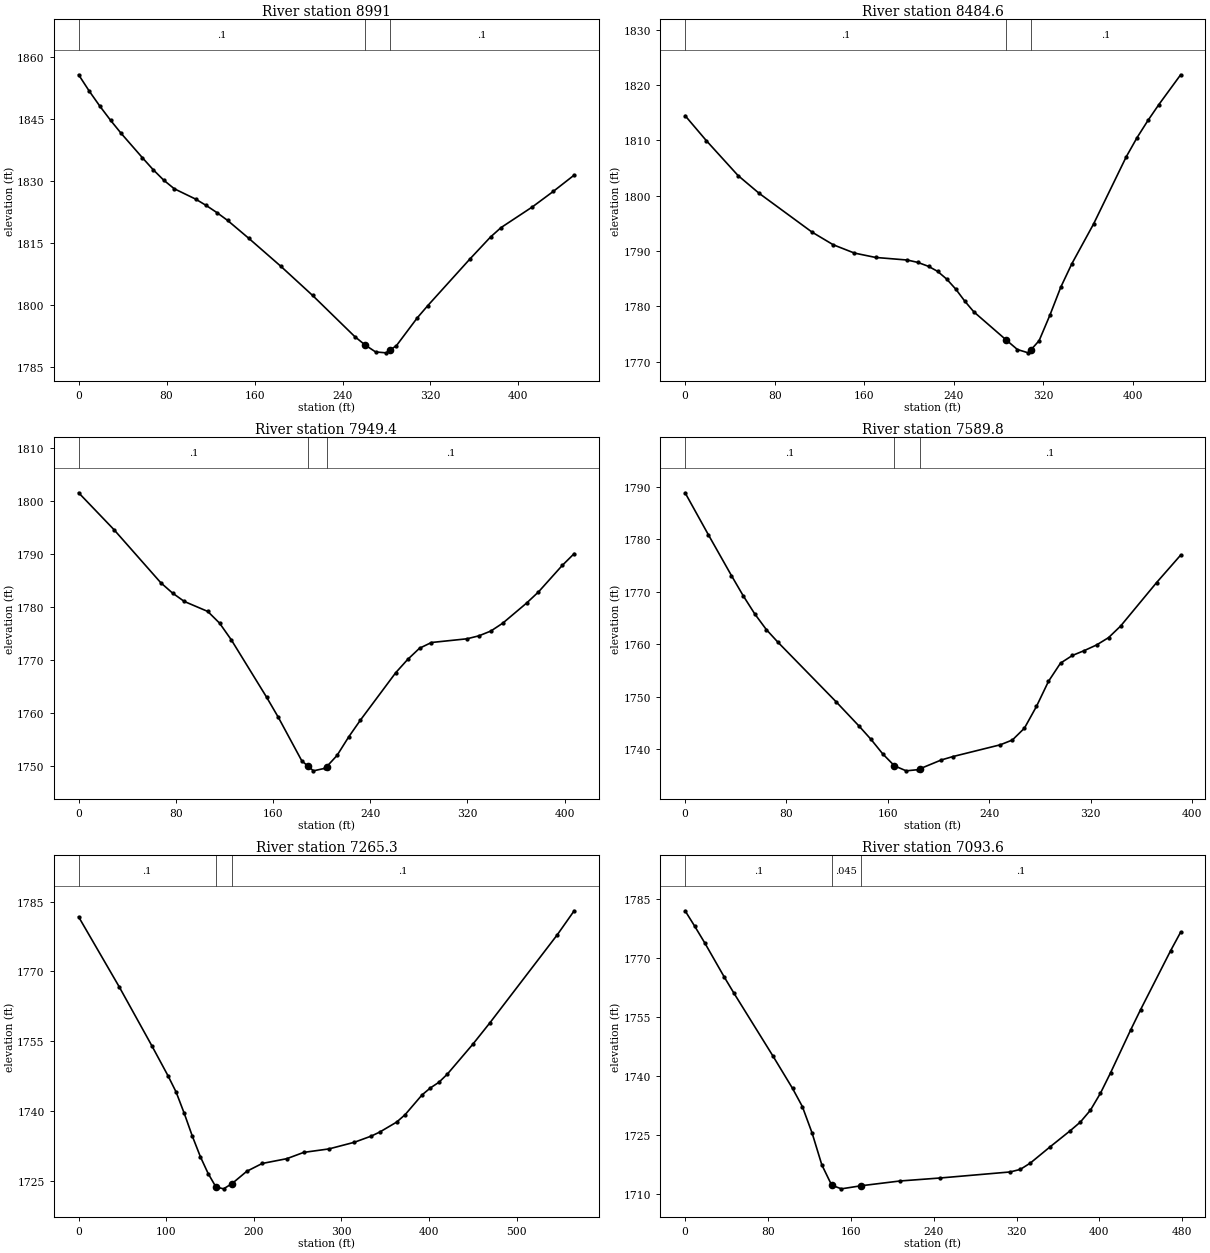
Type RM Length L Ch R = 1 ,8991    ,521.5,506.4,491.1
XS GIS Cut Line= 3
     1889558.166      413609.671     1889398.444      413778.074
     1889247.402       413936.06
#Sta/Elev= 30
       0 1855.73     9.7 1851.76    19.3 1848.13      29 1844.72    38.7 1841.53
      58 1835.64    67.7 1832.77    77.4  1830.2      87 1828.12   106.4 1825.62
     116 1824.08   125.7 1822.36   135.4 1820.47   154.7 1816.13   183.8 1809.37
   212.8 1802.28   251.1 1792.33   260.6 1790.27   270.1  1788.6   279.6 1788.38
  283.251789.056   289.1 1790.14   308.1 1796.89   317.6 1799.83   355.6 1811.03
   374.6 1816.43   384.2 1818.72   412.7 1823.73   431.7 1827.48   450.7 1831.43
#Mann= 3 , 0 , 0
       0      .1       0   260.6    .045       0  283.25      .1       0
Bank Sta=260.6,283.25
XS Rating Curve= 0 ,0
Exp/Cntr=0.3,0.1

Type RM Length L Ch R = 1 ,8484.6  ,517.7,535.3,552.2
XS GIS Cut Line= 4
     1889113.722      413394.393     1888964.416       413552.38
     1888943.583      413587.102     1888927.958       413771.13
#Sta/Elev= 30
       0 1814.46    18.9 1809.96    47.3 1803.64    66.2 1800.42   113.4 1793.42
   132.3 1791.14   151.2 1789.64   170.1 1788.85   198.5 1788.38   207.9 1787.95
   217.4 1787.24   225.5 1786.34   233.6 1784.95   241.7 1783.14   249.8 1780.96
   257.9 1779.02     287 1773.91   296.8 1772.22   306.5 1771.62  308.891772.162
   316.2 1773.82   325.9 1778.46   335.6 1783.51   345.4  1787.7   364.8 1794.88
     394 1807.02   403.7  1810.5   413.4 1813.59   423.1 1816.45   442.6 1821.84
#Mann= 3 , 0 , 0
       0      .1       0     287    .045       0  308.89      .1       0
Bank Sta=287,308.89
XS Rating Curve= 0 ,0
Exp/Cntr=0.3,0.1

Type RM Length L Ch R = 1 ,7949.4  ,364.7,359.5,354
XS GIS Cut Line= 3
     1888754.347      413132.241      1888556.43       413302.38
     1888485.249      413430.852
#Sta/Elev= 30
       0 1801.54      29 1794.62    67.7 1784.58    77.3 1782.65      87 1781.07
   106.3 1779.19     116 1776.99   125.7 1773.83   154.7 1763.05   164.3 1759.28
   183.7 1751.05   189.1 1749.99   193.3 1749.17     203 1749.66   204.1 1749.93
   212.7 1752.07   222.3 1755.56     232 1758.74     261 1767.65   270.8 1770.14
   280.6 1772.26   290.4 1773.34   319.7 1774.04   329.5  1774.6   339.3  1775.5
   349.1 1776.98   368.7 1780.76   378.5 1782.86   398.1 1787.86   407.9 1790.08
#Mann= 3 , 0 , 0
       0      .1       0   189.1    .045       0   204.1      .1       0
Bank Sta=189.1,204.1
XS Rating Curve= 0 ,0
Exp/Cntr=0.3,0.1

Type RM Length L Ch R = 1 ,7589.8  ,314.5,324.5,334.6
XS GIS Cut Line= 4
     1888473.097      412925.643     1888372.532      412989.373
     1888308.296      413079.651     1888233.513      413222.518
#Sta/Elev= 30
       0 1788.81    18.3 1780.85    36.6 1773.04    45.8 1769.23      55 1765.74
    64.1 1762.77    73.3 1760.35   119.1 1749.04   137.5 1744.34   146.8 1741.84
     156 1739.09   165.2 1736.83   174.5 1735.87   183.7 1736.09   185.1 1736.24
   202.2 1737.94   211.4 1738.59   248.8 1740.83   258.3 1741.74   267.8 1743.99
   277.3 1748.13   286.8 1752.91   296.3 1756.38   305.7 1757.84   315.2 1758.78
   324.7 1759.83   334.2 1761.23   343.7 1763.43   372.1 1771.71   391.1 1776.94
#Mann= 3 , 0 , 0
       0      .1       0   165.2    .045       0   185.1      .1       0
Bank Sta=165.2,185.1
XS Rating Curve= 0 ,0
Exp/Cntr=0.3,0.1

Type RM Length L Ch R = 1 ,7265.3  ,162.5,171.8,181
XS GIS Cut Line= 4
     1888259.685      412737.637     1888138.157      412805.345
     1888068.713       412843.54     1887983.643      413180.345
#Sta/Elev= 30
       0 1781.72    46.4 1766.67    83.5 1754.06     102  1747.6   111.3 1744.09
   120.6  1739.5   129.8 1734.62   139.1 1730.15   147.9 1726.57   156.7 1723.71
   165.5 1723.29   175.1 1724.41     192 1727.06   209.6 1728.74   237.7 1729.77
     257 1731.12   285.9 1731.87   314.9  1733.3   334.2 1734.63   343.8 1735.49
   363.1 1737.63   372.8 1739.23   392.1 1743.47   401.7 1744.98   411.4 1746.19
     421 1747.94     450 1754.34   469.3 1758.89   546.5 1777.87   565.8 1783.03
#Mann= 3 , 0 , 0
       0      .1       0   156.7    .045       0   175.1      .1       0
Bank Sta=156.7,175.1
XS Rating Curve= 0 ,0
Exp/Cntr=0.3,0.1

Type RM Length L Ch R = 1 ,7093.6  ,521.9,526.6,531.1
XS GIS Cut Line= 3
     1888219.624      412640.921     1888013.027      412660.018
     1887742.324      412649.095
#Sta/Elev= 28
       0    1782     9.4 1778.02    18.9 1773.86    37.7 1765.19    47.2 1761.01
    84.9    1745   103.7 1736.81   113.2 1732.18   122.6 1725.45     132 1717.34
   141.5 1712.17   150.9 1711.24   169.8 1712.02   207.5 1713.24   246.2    1714
   313.9 1715.54   323.6 1716.19   333.3  1717.8   352.6 1721.98     372 1726.07
   381.6 1728.24   391.3 1731.25     401 1735.58   410.7 1740.74     430 1751.59
   439.7 1756.82   468.7 1771.83   478.4 1776.55
#Mann= 3 , 0 , 0
       0      .1       0   141.5    .045       0   169.8      .1       0
Bank Sta=141.5,169.8
XS Rating Curve= 0 ,0
Exp/Cntr=0.3,0.1

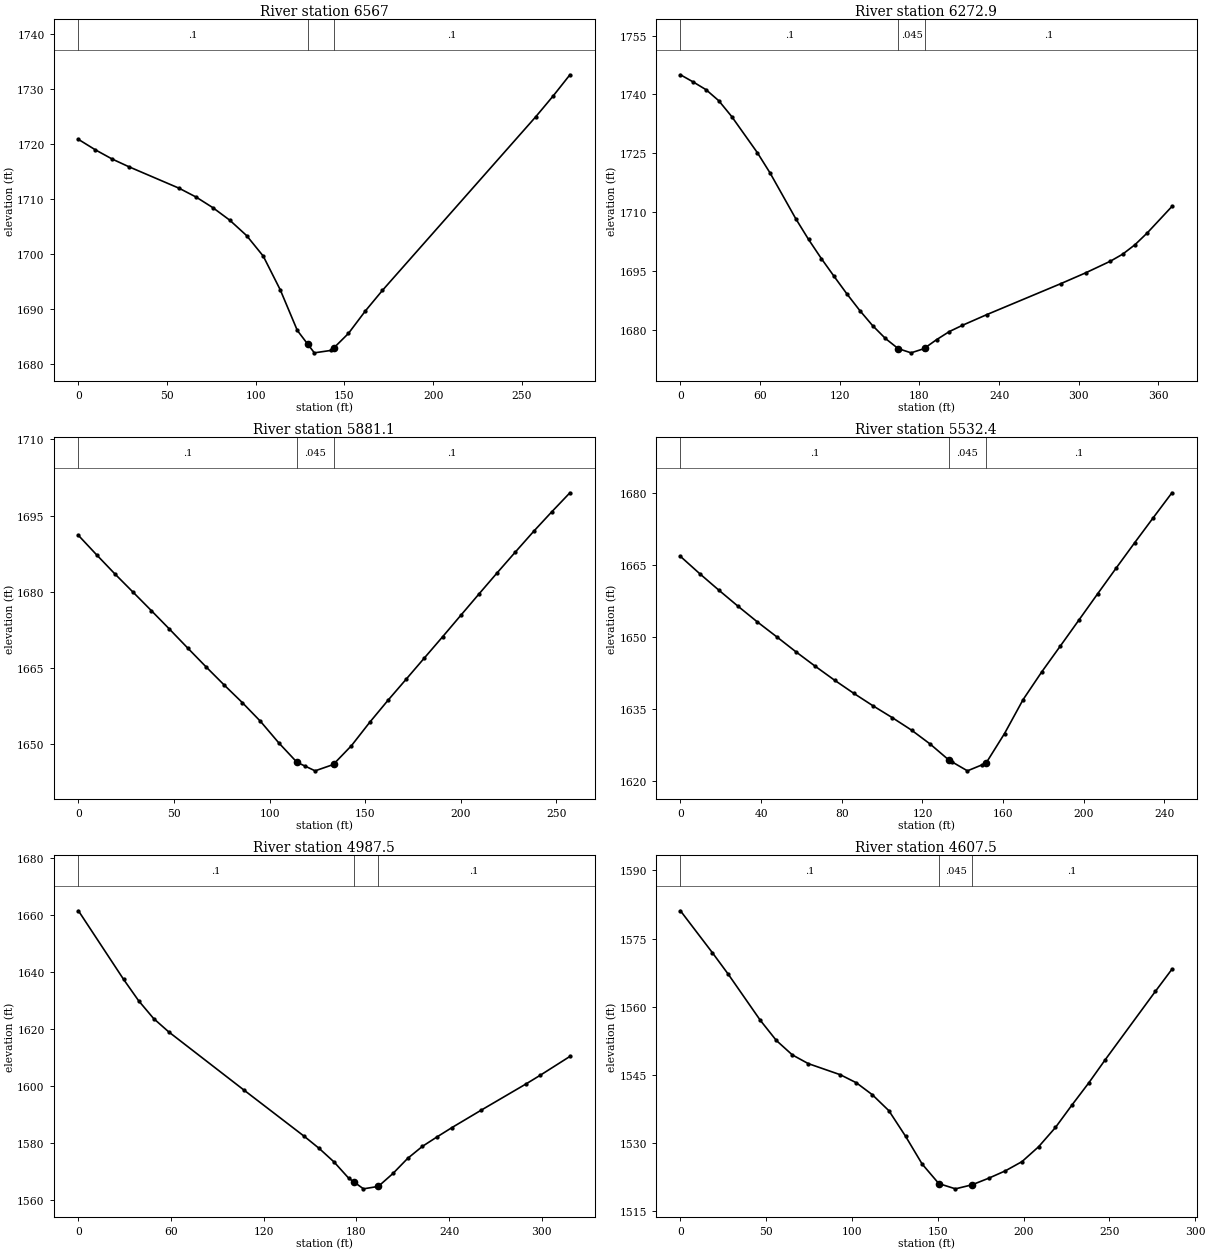
Type RM Length L Ch R = 1 ,6567    ,295.2,294.1,292.9
XS GIS Cut Line= 3
     1888186.638      412184.324     1888089.213      412147.303
     1887917.541      412127.032
#Sta/Elev= 22
       0 1720.83     9.5 1718.94      19 1717.26    28.4 1715.86    56.8 1711.94
    66.3 1710.35    75.8 1708.41    85.3 1706.14    94.8 1703.34   104.2  1699.6
   113.8 1693.46   123.4 1686.09   129.2 1683.62     133 1682.01   142.6 1682.46
   144.2 1682.97   152.2 1685.53   161.8 1689.64   171.4 1693.37   257.9 1724.97
   267.5 1728.67   277.1 1732.58
#Mann= 3 , 0 , 0
       0      .1       0   129.2    .045       0   144.2      .1       0
Bank Sta=129.2,144.2
XS Rating Curve= 0 ,0
Exp/Cntr=0.3,0.1

Type RM Length L Ch R = 1 ,6272.9  ,395.9,391.7,387.3
XS GIS Cut Line= 3
     1888341.152      411885.713     1888129.347      411871.824
      1887971.36      411871.824
#Sta/Elev= 30
       0 1745.03     9.6  1743.2    19.3 1741.22    28.9  1738.4    38.6 1734.38
    57.9 1725.17    67.5 1719.98    86.8 1708.34    96.5 1703.01   106.1 1698.15
   115.8 1693.56   125.4 1689.11   135.1 1684.87   144.7 1681.04   154.4 1677.74
     164 1675.16   173.7 1674.08   183.3 1675.13   184.5 1675.42     193 1677.46
   202.6 1679.52   212.3 1681.09   230.8 1683.84   286.6 1691.75   305.2 1694.49
   323.8 1697.46   333.1 1699.26   342.4 1701.68   351.7 1704.71   370.2 1711.43
#Mann= 3 , 0 , 0
       0      .1       0     164    .045       0   184.5      .1       0
Bank Sta=164,184.5
XS Rating Curve= 0 ,0
Exp/Cntr=0.3,0.1

Type RM Length L Ch R = 1 ,5881.1  ,353.7,348.7,343.8
XS GIS Cut Line= 2
     1888210.944      411479.463     1887955.735      411510.713
#Sta/Elev= 30
       0  1691.1     9.5 1687.28      19 1683.54    28.6 1679.91    38.1  1676.3
    47.6 1672.65    57.1 1668.94    66.7 1665.23    76.2 1661.65    85.7 1658.18
    95.2 1654.49   104.8 1650.24   114.3 1646.42   118.7 1645.64   123.8 1644.73
   133.3 1645.97   133.7 1646.13   142.8 1649.68   152.4  1654.3   161.9 1658.61
   171.4 1662.76   180.9 1666.93   190.5 1671.13     200 1675.35   209.5 1679.55
     219 1683.71   228.6 1687.84   238.1 1691.88   247.6 1695.74   257.1 1699.49
#Mann= 3 , 0 , 0
       0      .1       0   114.3    .045       0   133.7      .1       0
Bank Sta=114.3,133.7
XS Rating Curve= 0 ,0
Exp/Cntr=0.3,0.1

Type RM Length L Ch R = 1 ,5532.4  ,548.3,544.8,541
XS GIS Cut Line= 3
     1888082.472      411170.435     1887967.888      411173.907
      1887846.36       411217.31
#Sta/Elev= 29
       0 1666.76     9.6 1663.14    19.1  1659.7    28.7 1656.32    38.2 1653.08
    47.8 1649.98    57.3 1646.86    66.9 1643.84    76.4 1640.96      86  1638.2
    95.5 1635.61   105.1 1633.13   114.6 1630.54   123.8 1627.65   133.1 1624.31
   134.6 1623.94   142.3 1622.06   149.6 1623.32   151.5 1623.65   160.7 1629.84
   169.9 1636.91   179.2 1642.72   188.4  1648.1   197.6 1653.51   206.8 1658.93
     216  1664.3   225.2  1669.6   234.5 1674.86   243.7 1680.02
#Mann= 3 , 0 , 0
       0      .1       0   133.1    .045       0   151.5      .1       0
Bank Sta=133.1,151.5
XS Rating Curve= 0 ,0
Exp/Cntr=0.3,0.1

Type RM Length L Ch R = 1 ,4987.5  ,379.3,380,380.5
XS GIS Cut Line= 3
     1888077.263      410600.991     1887924.485      410632.241
     1887782.124      410710.366
#Sta/Elev= 22
       0 1661.44    29.2 1637.41      39 1629.86    48.7 1623.62    58.5 1618.93
   107.2 1598.52   146.2 1582.31   155.9 1578.05   165.5 1573.31     175 1567.61
   178.4 1566.28   184.6 1563.86   194.2 1564.71   203.7 1569.25   213.2 1574.54
   222.8 1578.78   232.4 1582.14   241.9 1585.36     261 1591.52   289.7 1600.62
   299.2 1603.76   318.3 1610.33
#Mann= 3 , 0 , 0
       0      .1       0   178.4    .045       0   194.2      .1       0
Bank Sta=178.4,194.2
XS Rating Curve= 0 ,0
Exp/Cntr=0.3,0.1

Type RM Length L Ch R = 1 ,4607.5  ,202.7,211.2,219.7
XS GIS Cut Line= 3
     1887878.826      410272.432     1887768.149      410288.057
     1887613.201      410368.786
#Sta/Elev= 27
       0  1581.1    18.6 1571.89    27.9 1567.13    46.6 1556.98    55.9 1552.57
    65.2  1549.4    74.5 1547.48    93.2 1545.03   102.5 1543.27   111.8 1540.65
   121.5 1537.12   131.2 1531.51   140.9 1525.38   150.6 1521.09     151 1521.04
   160.3 1519.93     170 1520.82   179.7 1522.27   189.4 1523.89   199.1 1525.92
   208.8  1529.2   218.6 1533.43   228.2 1538.36     238 1543.23   247.7 1548.38
   276.8 1563.35   286.5 1568.24
#Mann= 3 , 0 , 0
       0      .1       0     151    .045       0     170      .1       0
Bank Sta=151,170
XS Rating Curve= 0 ,0
Exp/Cntr=0.3,0.1

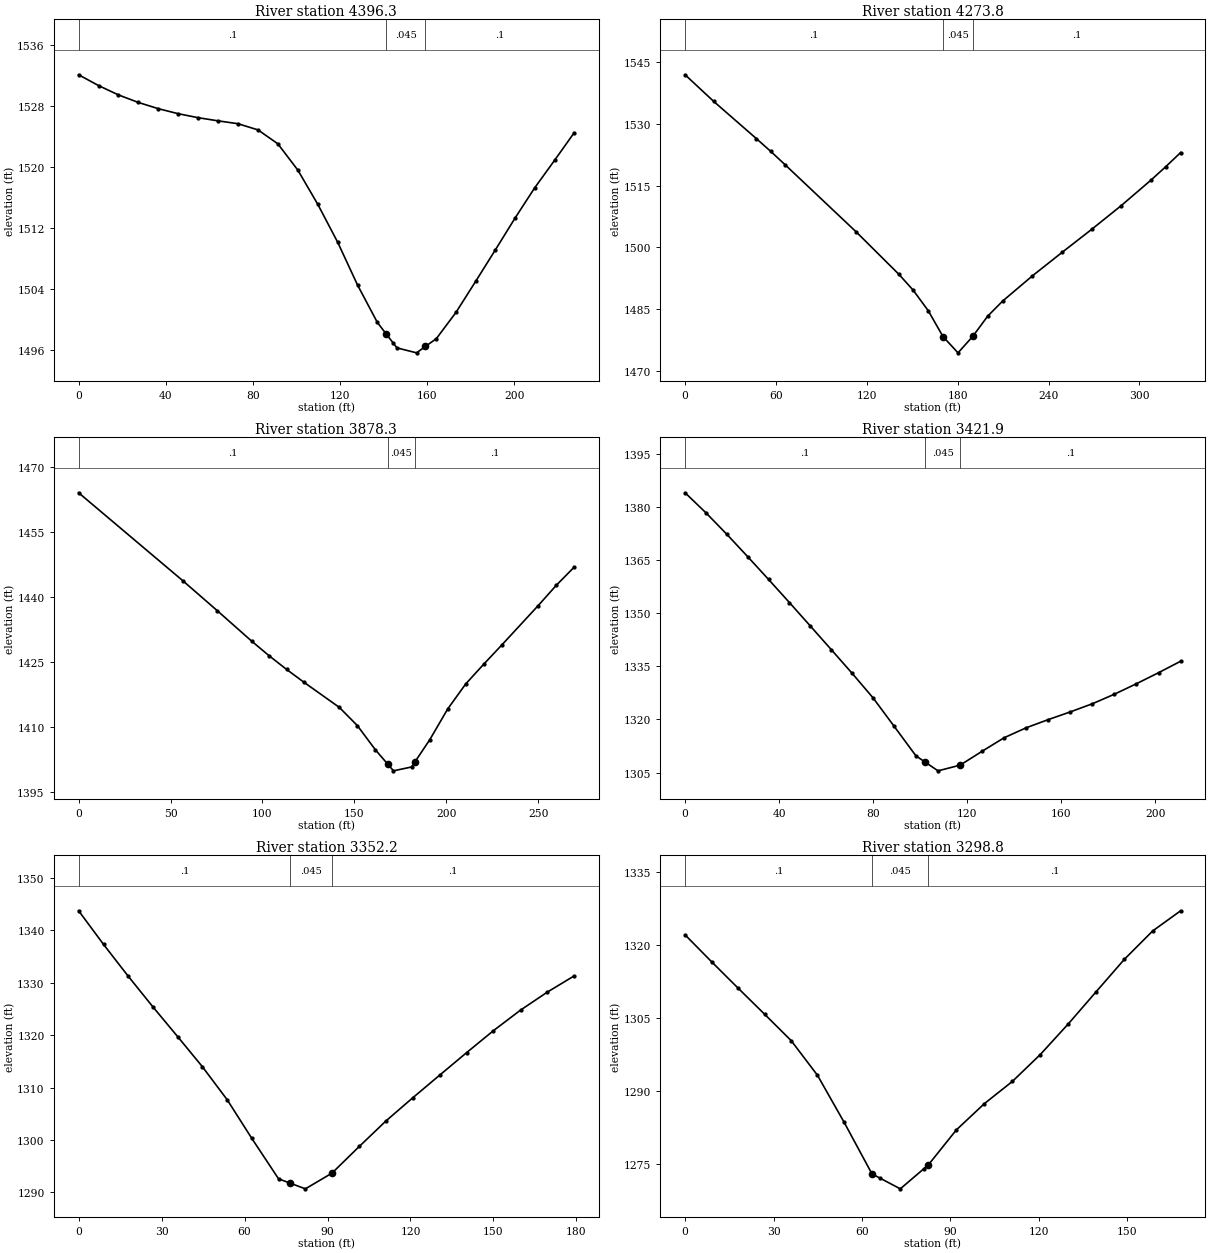
Type RM Length L Ch R = 1 ,4396.3  ,119.2,122.5,125.2
XS GIS Cut Line= 3
     1887777.914      410177.777     1887663.331      410120.486
     1887564.373      410130.902
#Sta/Elev= 29
       0 1532.07     9.2 1530.65    18.3 1529.43    27.4 1528.45    36.6 1527.63
    45.8 1526.97    54.9 1526.45      64 1526.04    73.2 1525.66    82.4 1524.85
    91.5 1523.03   100.7 1519.58   109.8 1515.13     119 1510.13   128.1 1504.54
   137.2 1499.64   141.31498.121   144.3 1497.01   146.2 1496.31   155.2 1495.66
   159.3  1496.5   164.3 1497.52   173.3 1500.95   182.4 1505.04   191.4 1509.14
   200.5 1513.33   209.5 1517.28   218.6 1520.87   227.6 1524.48
#Mann= 3 , 0 , 0
       0      .1       0   141.3    .045       0   159.3      .1       0
Bank Sta=141.3,159.3
XS Rating Curve= 0 ,0
Exp/Cntr=0.3,0.1

Type RM Length L Ch R = 1 ,4273.8  ,405.1,395.5,385.7
XS GIS Cut Line= 4
     1887822.923      410072.779     1887689.242      410003.334
     1887630.215      410001.598     1887519.103      410039.793
#Sta/Elev= 21
       0 1542.01    18.8 1535.56    47.1 1526.46    56.5 1523.38    65.9 1520.16
     113 1503.76   141.2 1493.43   150.6 1489.58   160.5 1484.61   170.3 1478.28
   180.2 1474.33     190 1478.36   199.8 1483.26   209.7 1486.94   229.3 1493.06
   248.9 1498.78   268.4 1504.37     288 1510.17   307.6 1516.37   317.4 1519.65
   327.2 1523.08
#Mann= 3 , 0 , 0
       0      .1       0   170.3    .045       0     190      .1       0
Bank Sta=170.3,190
XS Rating Curve= 0 ,0
Exp/Cntr=0.3,0.1

Type RM Length L Ch R = 1 ,3878.3  ,455.3,456.5,455.5
XS GIS Cut Line= 3
     1887792.541      409599.255     1887660.597      409600.991
      1887533.86       409654.81
#Sta/Elev= 22
       0 1464.14    56.6 1443.88    75.4 1436.95    94.2 1429.89   103.7 1426.52
   113.1  1423.4   122.5 1420.45   141.8 1414.64   151.6 1410.45   161.5 1404.82
   168.1 1401.57   171.3 1399.99   181.1 1400.88   183.1 1402.14     191 1407.14
   200.8 1414.27   210.6 1420.04   220.5 1424.64   230.3 1429.06     250  1438.1
   259.8 1442.76   269.6 1446.99
#Mann= 3 , 0 , 0
       0      .1       0   168.1    .045       0   183.1      .1       0
Bank Sta=168.1,183.1
XS Rating Curve= 0 ,0
Exp/Cntr=0.3,0.1

Type RM Length L Ch R = 1 ,3421.9  ,69.5,69.7,69.8
XS GIS Cut Line= 3
     1887717.888       409188.23     1887629.347      409181.286
     1887518.235      409231.633
#Sta/Elev= 26
       0 1384.01     8.9 1378.34    17.8 1372.25    26.6 1365.99    35.5 1359.54
    44.4    1353    53.3 1346.37    62.2 1339.71      71 1333.07    79.9 1326.14
    88.8 1318.18    98.2 1309.72   102.1 1307.96   107.6 1305.49     117  1307.1
   117.1 1307.14   126.4 1311.04   135.7 1314.83   145.1 1317.65   154.5 1319.96
   163.9 1322.14   173.3 1324.45   182.6 1327.12     192 1330.09   201.4  1333.2
   210.8 1336.44
#Mann= 3 , 0 , 0
       0      .1       0   102.1    .045       0   117.1      .1       0
Bank Sta=102.1,117.1
XS Rating Curve= 0 ,0
Exp/Cntr=0.3,0.1

Type RM Length L Ch R = 1 ,3352.2  ,53.6,53.4,52.5
XS GIS Cut Line= 3
     1887664.056      409126.891     1887602.207      409117.125
      1887495.87      409164.868
#Sta/Elev= 21
       0 1343.72       9 1337.31    17.9 1331.26    26.8 1325.43    35.8 1319.72
    44.7 1314.01    53.7 1307.69    62.6 1300.32    72.3 1292.59    76.6 1291.74
      82 1290.68    91.6 1293.67   101.5 1298.77   111.2 1303.66   120.9 1308.08
   130.6 1312.38   140.3 1316.66     150 1320.85   159.8 1324.77   169.5 1328.21
   179.2  1331.3
#Mann= 3 , 0 , 0
       0      .1       0    76.6    .045       0    91.6      .1       0
Bank Sta=76.6,91.6
XS Rating Curve= 0 ,0
Exp/Cntr=0.3,0.1

Type RM Length L Ch R = 1 ,3298.8  ,104.8,114.3,125.5
XS GIS Cut Line= 3
     1887637.289      409070.139      1887583.47      409066.666
     1887481.039      409117.014
#Sta/Elev= 21
       0 1322.16       9 1316.62      18 1311.18      27 1305.81      36 1300.38
    44.9 1293.26    53.9 1283.63    63.4 1272.95      66 1272.12      73 1269.88
      81 1274.02    82.5  1274.8      92    1282   101.5 1287.41     111 1291.98
   120.5 1297.53     130 1303.84   139.5  1310.5     149 1317.12   158.6 1322.96
   168.1 1327.12
#Mann= 3 , 0 , 0
       0      .1       0    63.4    .045       0    82.5      .1       0
Bank Sta=63.4,82.5
XS Rating Curve= 0 ,0
Exp/Cntr=0.3,0.1

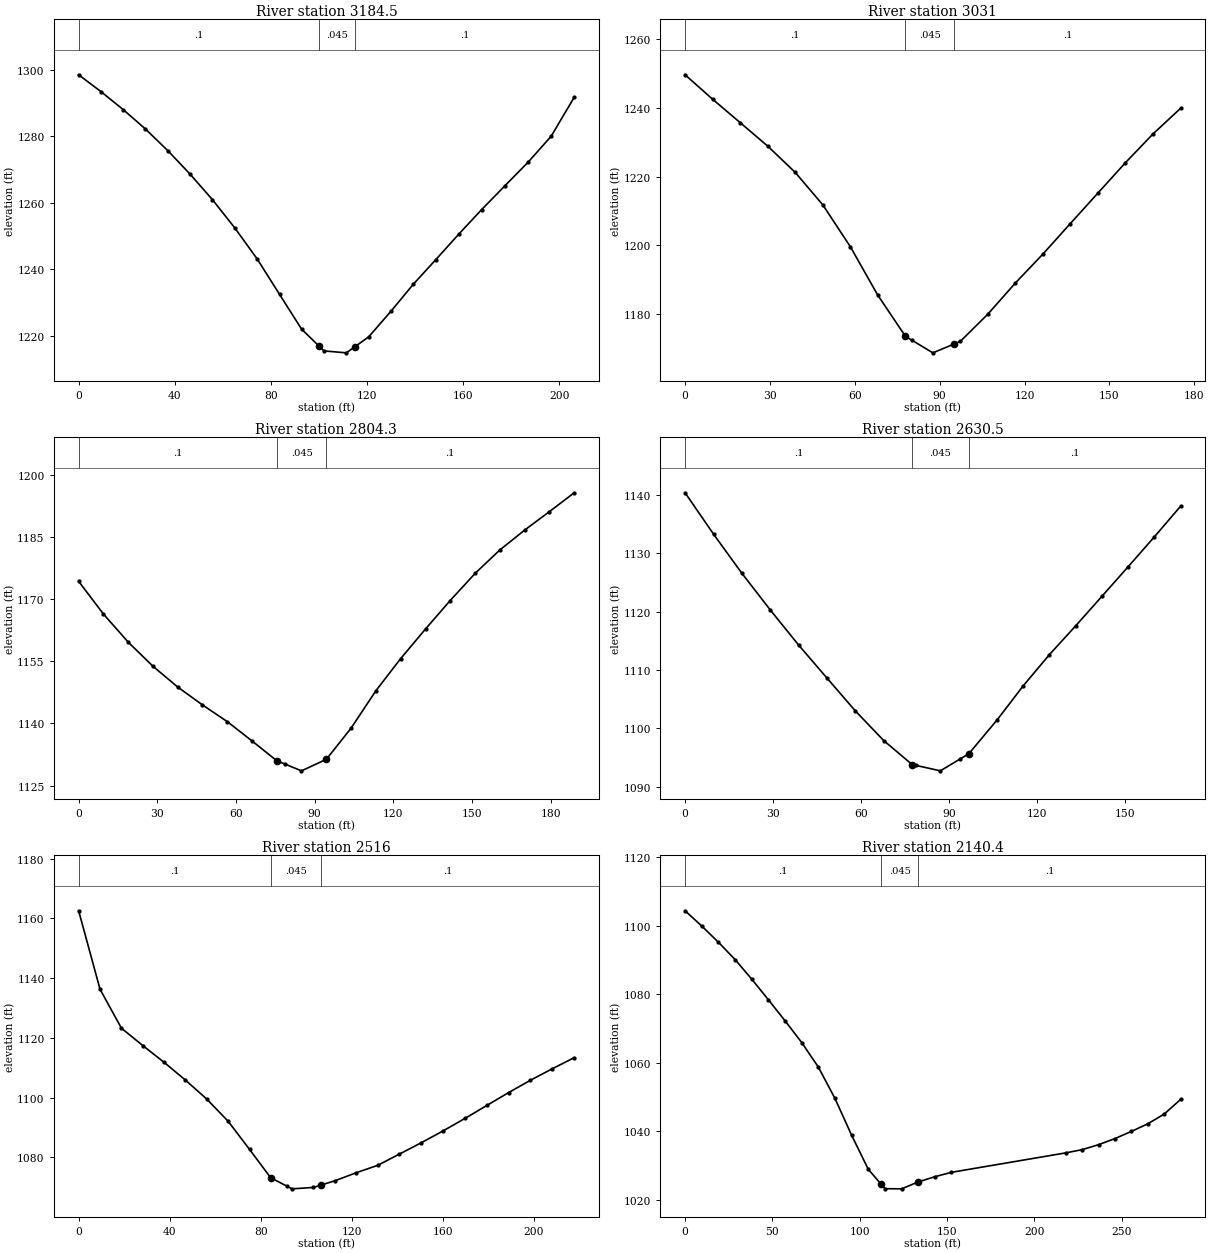
Type RM Length L Ch R = 1 ,3184.5  ,146.5,153.4,160.3
XS GIS Cut Line= 3
     1887637.289      408971.289     1887488.852       408966.08
     1887434.164       408984.31
#Sta/Elev= 25
       0 1298.42     9.3 1293.35    18.6 1287.92    27.8 1282.12    37.1 1275.62
    46.4 1268.53    55.7 1260.86      65 1252.36    74.3 1243.04    83.6  1232.4
    92.8 1221.92     100 1216.87   102.1  1215.4   111.4 1214.82     115 1216.68
   120.7 1219.62     130 1227.35   139.2 1235.39   148.5 1242.74   158.1 1250.44
   167.7 1257.89   177.4 1265.06     187 1272.12   196.6 1279.91   206.2 1291.63
#Mann= 3 , 0 , 0
       0      .1       0     100    .045       0     115      .1       0
Bank Sta=100,115
XS Rating Curve= 0 ,0
Exp/Cntr=0.3,0.1

Type RM Length L Ch R = 1 ,3031    ,230,226.7,223.3
XS GIS Cut Line= 2
     1887641.499      408847.518     1887476.569      408788.491
#Sta/Elev= 21
       0 1249.71     9.7  1242.6    19.5 1235.74    29.2 1228.91    38.9 1221.28
    48.7 1211.76    58.4 1199.61    68.1 1185.48    77.9 1173.45    80.2 1172.31
    87.6 1168.63    95.2 1171.24    97.3 1171.96     107 1179.88   116.8 1189.02
   126.5 1197.42   136.2 1206.32     146 1215.26   155.7 1224.09   165.4 1232.43
   175.2 1239.95
#Mann= 3 , 0 , 0
       0      .1       0    77.9    .045       0    95.2      .1       0
Bank Sta=77.9,95.2
XS Rating Curve= 0 ,0
Exp/Cntr=0.3,0.1

Type RM Length L Ch R = 1 ,2804.3  ,162.3,173.8,182.6
XS GIS Cut Line= 2
      1887710.29      408620.338     1887524.966       408583.38
#Sta/Elev= 23
       0  1174.3     9.4 1166.44    18.9 1159.62    28.4 1153.77    37.8 1148.78
    47.2 1144.49    56.7 1140.44    66.1  1135.8    75.6 1130.99    78.8 1130.17
      85 1128.57    93.8 1131.15    94.5 1131.36   103.9 1138.86   113.4 1147.91
   122.8 1155.63   132.3 1162.79   141.7 1169.65   151.2 1176.19   160.6 1181.83
   170.1 1186.64   179.5 1191.07     189 1195.65
#Mann= 3 , 0 , 0
       0      .1       0    75.6    .045       0    94.5      .1       0
Bank Sta=75.6,94.5
XS Rating Curve= 0 ,0
Exp/Cntr=0.3,0.1

Type RM Length L Ch R = 1 ,2630.5  ,118.6,114.5,113
XS GIS Cut Line= 3
     1887749.268       408497.33     1887667.237      408429.622
     1887604.737      408429.622
#Sta/Elev= 21
       0 1140.33     9.7 1133.25    19.3 1126.59      29  1120.3    38.7 1114.27
    48.4  1108.6      58 1103.02    67.7 1097.93    77.4 1093.82    78.7 1093.68
      87 1092.75    93.7 1094.77    96.7 1095.67   106.4  1101.5   115.3 1107.33
   124.2 1112.65   133.2  1117.6   142.1 1122.63     151 1127.67   159.9 1132.76
   168.9 1138.04
#Mann= 3 , 0 , 0
       0      .1       0    77.4    .045       0    96.7      .1       0
Bank Sta=77.4,96.7
XS Rating Curve= 0 ,0
Exp/Cntr=0.3,0.1

Type RM Length L Ch R = 1 ,2516    ,401.2,375.6,348.9
XS GIS Cut Line= 3
     1887842.888      408406.546     1887728.305       408342.31
     1887643.235      408357.935
#Sta/Elev= 26
       0 1162.56     9.4 1136.31    18.8 1123.26    28.2 1117.45    37.5 1111.86
    46.9 1105.91    56.3 1099.54    65.7 1092.11    75.1  1082.7    84.4  1073.2
    91.4 1070.43    93.8 1069.48   103.2 1069.95   106.4 1070.71   112.6 1072.17
     122 1074.87   131.4 1077.33     141 1081.12   150.6 1084.91   160.2 1088.88
   169.8 1093.05   179.4 1097.39     189 1101.71   198.6 1105.84   208.2 1109.69
   217.8 1113.38
#Mann= 3 , 0 , 0
       0      .1       0    84.4    .045       0   106.4      .1       0
Bank Sta=84.4,106.4
XS Rating Curve= 0 ,0
Exp/Cntr=0.3,0.1

Type RM Length L Ch R = 1 ,2140.4  ,372.6,380.9,389.1
XS GIS Cut Line= 3
     1887790.805      407925.643     1887674.485      408008.977
     1887592.888       408123.56
#Sta/Elev= 26
       0 1104.37     9.5 1099.93    19.1 1095.18    28.6 1090.14    38.2 1084.39
    47.7 1078.38    57.2 1072.27    66.8 1065.88    76.3 1058.73    85.8 1049.59
    95.4 1038.78   104.9 1028.88   112.3  1024.5   114.5  1023.2     124 1023.16
   133.6 1025.19   143.1 1026.72   152.5 1027.98   218.1 1033.67   227.5 1034.62
   236.9 1036.07   246.2 1037.85   255.6 1039.93     265 1042.16   274.4    1045
   283.8 1049.28
#Mann= 3 , 0 , 0
       0      .1       0   112.3    .045       0   133.6      .1       0
Bank Sta=112.3,133.6
XS Rating Curve= 0 ,0
Exp/Cntr=0.3,0.1

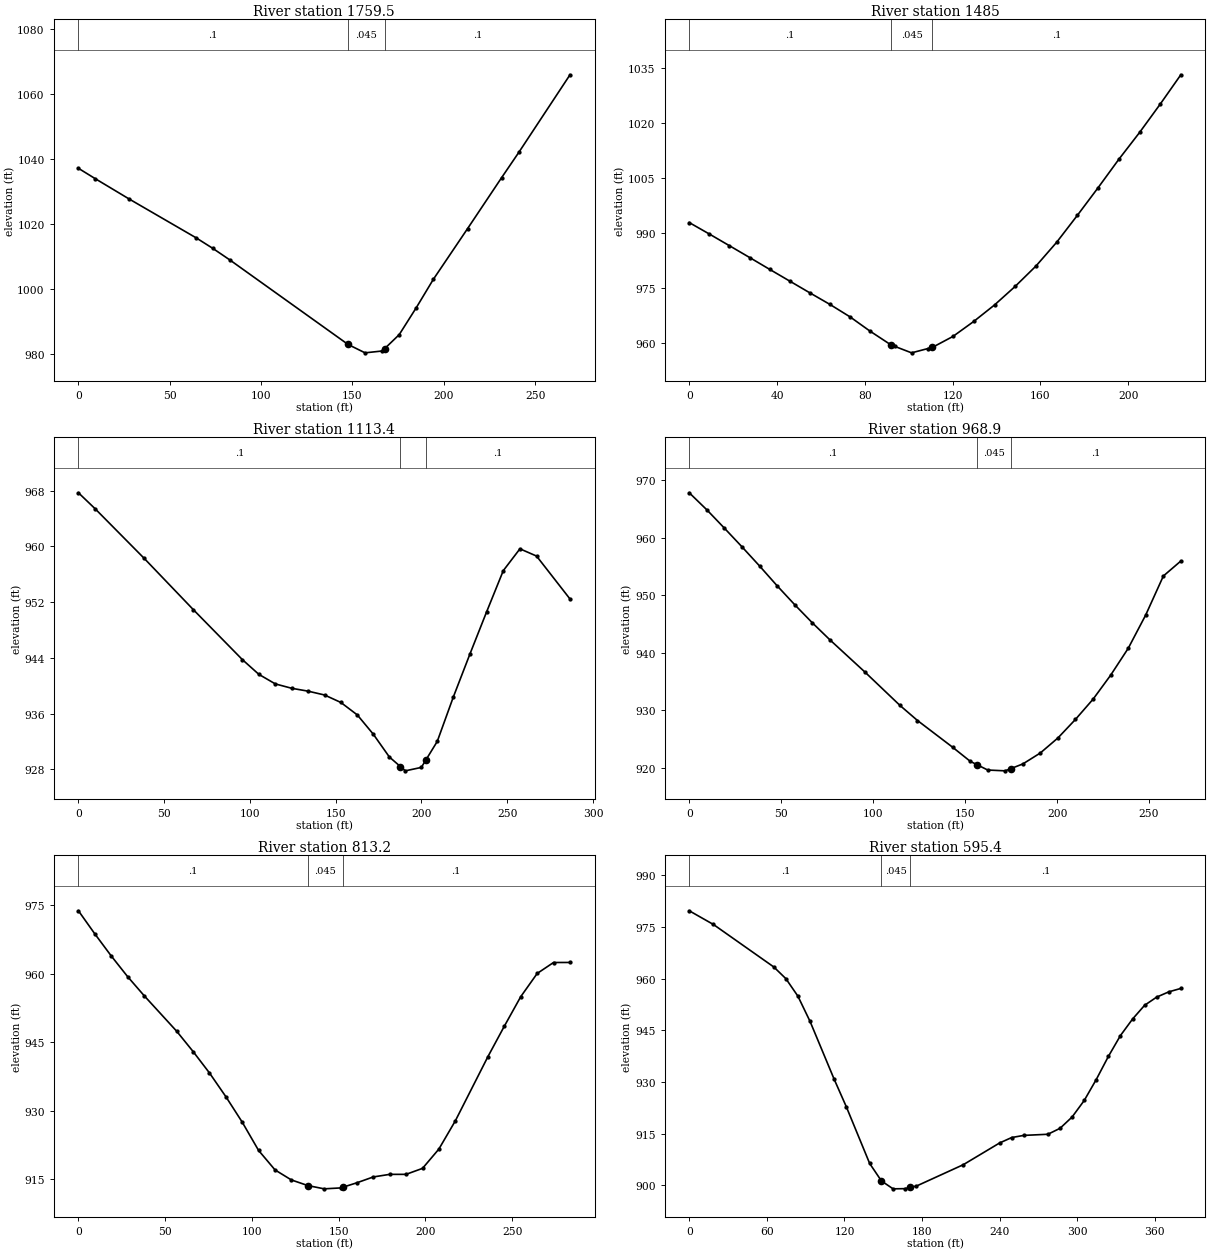
Type RM Length L Ch R = 1 ,1759.5  ,280.8,274.6,266.5
XS GIS Cut Line= 3
     1887603.305      407778.074     1887474.833      407767.657
     1887339.416      407804.116
#Sta/Elev= 17
       0  1037.2     9.2 1034.01    27.6 1027.81    64.4 1015.81    73.6 1012.54
    82.9 1008.99   147.6  982.98   156.9   980.4   166.3  980.97   167.7  981.73
   175.6     986     185  994.35   194.3 1003.04     213 1018.62   231.7 1034.36
   241.1 1042.13   269.1 1065.99
#Mann= 3 , 0 , 0
       0      .1       0   147.6    .045       0   167.7      .1       0
Bank Sta=147.6,167.7
XS Rating Curve= 0 ,0
Exp/Cntr=0.3,0.1

Type RM Length L Ch R = 1 ,1485    ,348.6,371.6,394.1
XS GIS Cut Line= 3
     1887496.664      407475.195     1887417.237       407497.33
      1887300.05      407576.757
#Sta/Elev= 27
       0  992.79     9.2  989.65    18.3  986.48    27.5  983.26    36.6  980.04
    45.8  976.82      55   973.6    64.1  970.46    73.3  967.05    82.4  963.16
    91.9  959.42    93.7     959   101.3  957.25   108.7  958.41   110.8  958.74
   120.2  961.74   129.6   965.8   139.1  970.31   148.5  975.37     158  980.94
   167.4   987.4   176.8  994.72   186.3  1002.3   195.7 1010.01   205.2 1017.37
   214.6  1025.1     224 1033.11
#Mann= 3 , 0 , 0
       0      .1       0    91.9    .045       0   110.8      .1       0
Bank Sta=91.9,110.8
XS Rating Curve= 0 ,0
Exp/Cntr=0.3,0.1

Type RM Length L Ch R = 1 ,1113.4  ,137,144.4,151.7
XS GIS Cut Line= 4
     1887421.013      407264.185       1887268.8      407206.966
     1887217.398      407184.842      1887149.69      407190.918
#Sta/Elev= 26
       0  967.69     9.6  965.43    38.3  958.29      67  950.92    95.6  943.75
   105.2  941.64   114.8  940.27   124.4  939.64   133.9  939.23   143.5  938.68
     153  937.61   162.6  935.82   171.9  933.06   181.3  929.78   187.7  928.42
   190.6   927.8   199.9  928.29   202.7  929.41   209.2  932.02   218.6  938.41
   228.3  944.59     238  950.62   247.7  956.52   257.4  959.65   267.1  958.61
   286.6  952.45
#Mann= 3 , 0 , 0
       0      .1       0   187.7    .045       0   202.7      .1       0
Bank Sta=187.7,202.7
XS Rating Curve= 0 ,0
Exp/Cntr=0.3,0.1

Type RM Length L Ch R = 1 ,968.9   ,159.1,155.8,152.5
XS GIS Cut Line= 2
     1887458.904      407200.455     1887260.987      407020.768
#Sta/Elev= 28
       0   967.8     9.6  964.83    19.1  961.66    28.6  958.44    38.2   955.1
    47.7  951.68    57.3  948.38    66.8  945.26    76.4  942.29    95.5  936.68
   114.6  930.87   124.1  928.26   143.2  923.62   152.8  921.17  156.41920.5975
   162.3  919.66   171.8  919.52   174.8   919.9   181.4  920.72   190.9  922.62
   200.5  925.24     210  928.45   219.6  931.97   229.1  936.11   238.7   940.8
   248.2  946.58   257.8  953.35   267.3  955.95
#Mann= 3 , 0 , 0
       0      .1       0  156.41    .045       0   174.8      .1       0
Bank Sta=156.41,174.8
XS Rating Curve= 0 ,0
Exp/Cntr=0.3,0.1

Type RM Length L Ch R = 1 ,813.2   ,243.8,217.7,192.8
XS GIS Cut Line= 3
     1887570.449      407066.956     1887405.084      406957.581
     1887320.449      406949.768
#Sta/Elev= 30
       0  973.73     9.4   968.7    18.9  963.85    28.3  959.34    37.8  955.18
    56.6  947.38    66.1  942.92    75.5  938.25      85  933.03    94.4  927.47
   103.8   921.3   113.3  917.02   122.7  914.83   132.2   913.6   141.6  912.88
   151.1  913.08   152.2  913.21   160.5  914.21   169.9  915.48   179.4  916.05
   188.8  916.05   198.3  917.36   207.7  921.57   217.2  927.75     236  941.82
   245.5  948.51   254.9  954.93   264.4  960.02   273.8  962.41   283.3  962.42
#Mann= 3 , 0 , 0
       0      .1       0   132.2    .045       0   152.2      .1       0
Bank Sta=132.2,152.2
XS Rating Curve= 0 ,0
Exp/Cntr=0.3,0.1

Type RM Length L Ch R = 1 ,595.4   ,396.2,395,392.1
XS GIS Cut Line= 4
     1887625.874      406725.991     1887509.555      406760.713
     1887433.166      406809.324      1887315.11      406929.116
#Sta/Elev= 30
       0  979.72    18.7  975.74    65.4   963.4    74.7  960.02      84  954.94
    93.4  947.61     112  930.86   121.4  922.87   139.5  906.37   148.6   901.3
   157.6  899.01   166.6  899.06  170.78899.4091   175.7  899.82   211.9  906.02
     240  912.33   249.3   913.9   258.6  914.52   277.3  914.85   286.7  916.58
     296  919.85   305.4  924.66   314.7  930.74   324.1  937.46   333.4   943.5
   342.8  948.31   352.1  952.29   361.4  954.66   370.8  956.19   380.1  957.18
#Mann= 3 , 0 , 0
       0      .1       0   148.6    .045       0  170.78      .1       0
Bank Sta=148.6,170.78
XS Rating Curve= 0 ,0
Exp/Cntr=0.3,0.1

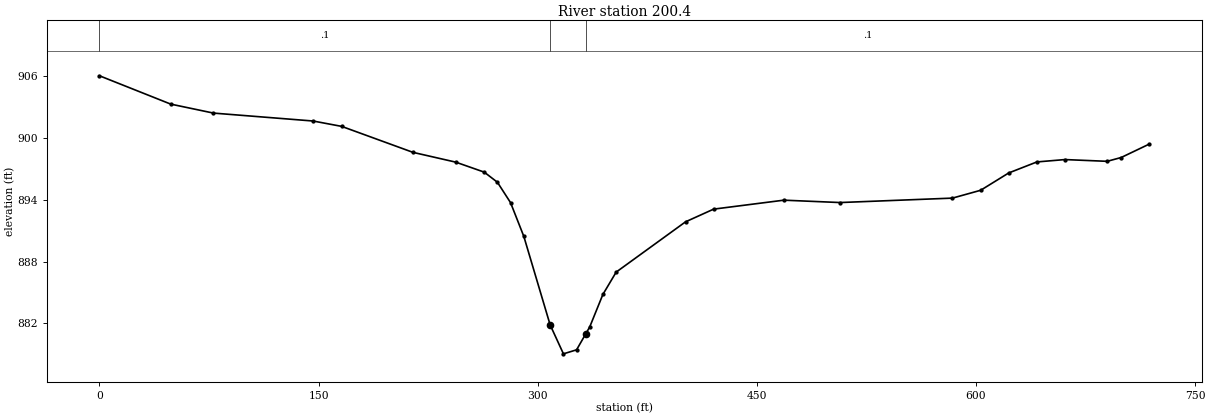
Type RM Length L Ch R = 1 ,200.4   ,203.7,200.4,197
XS GIS Cut Line= 4
     1887388.027      406512.449     1887157.124      406639.185
     1887077.263      406698.213     1887078.999      407054.116
#Sta/Elev= 30
       0  906.03    48.8  903.28      78  902.41   146.3  901.64   165.8  901.12
   214.6   898.6   243.9  897.65   263.4  896.68   272.4   895.7   281.4  893.72
   290.5  890.44   308.5  881.86   317.6  879.05   326.6  879.44     333  881.02
   335.6  881.66   344.6  884.81   353.7  886.98   401.2  891.86   420.4  893.09
   468.5  893.96     507  893.73   583.9  894.16   603.2  894.92   622.4   896.6
   641.7  897.67   660.9   897.9   689.8  897.73   699.4   898.1   718.6   899.4
#Mann= 3 , 0 , 0
       0      .1       0   308.5    .045       0     333      .1       0
Bank Sta=308.5,333
XS Rating Curve= 0 ,0
Exp/Cntr=0.3,0.1